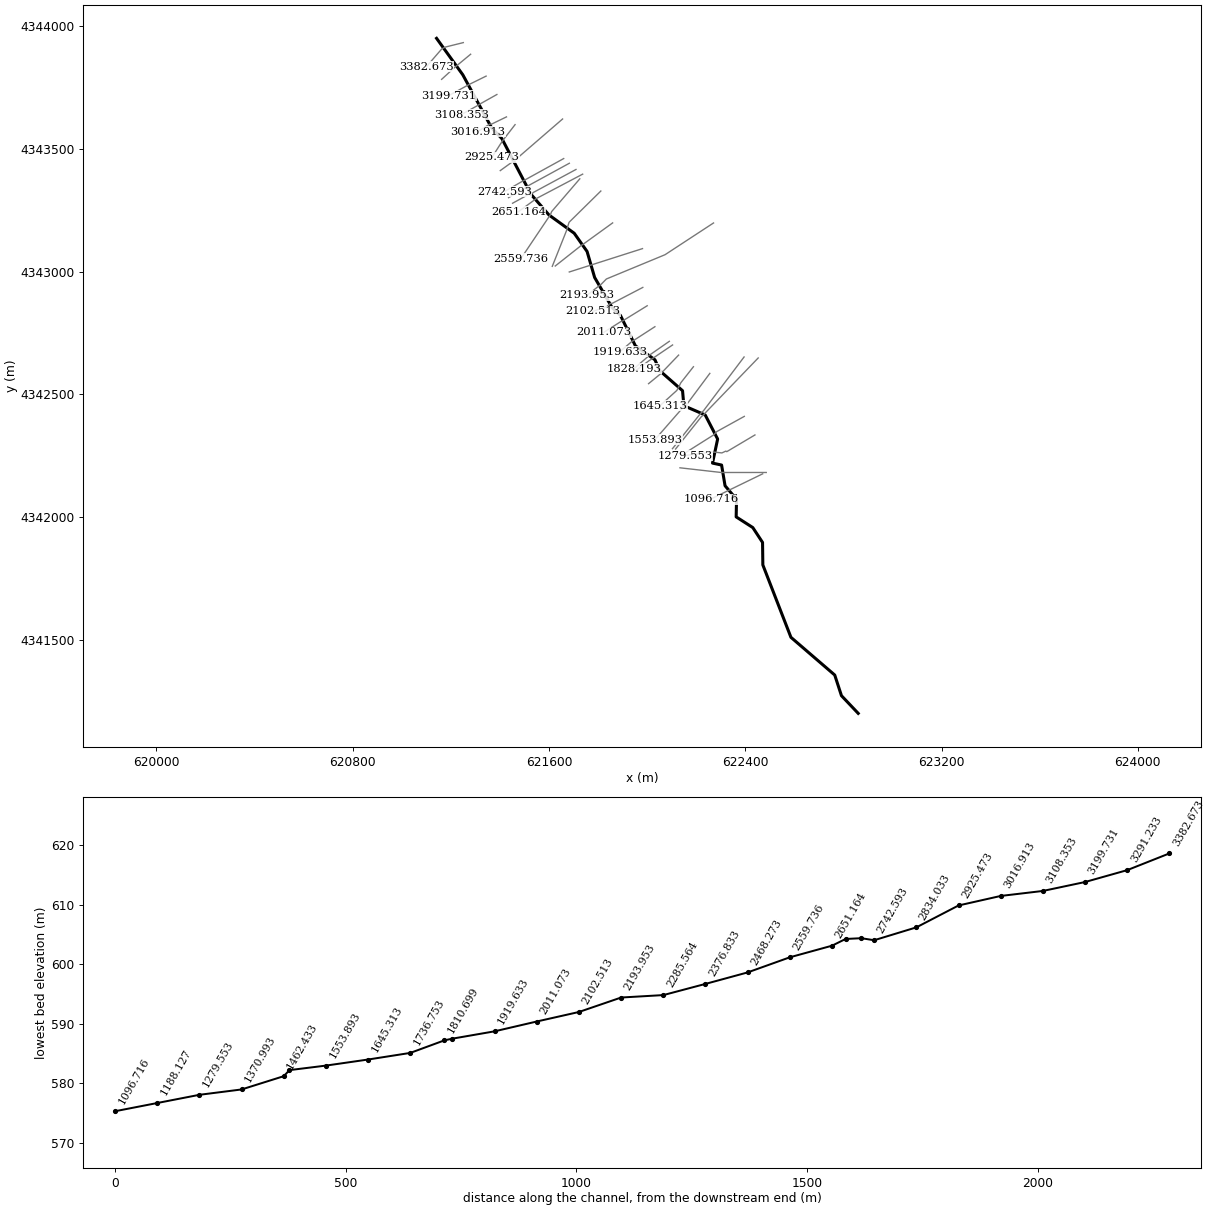
--- ThunderstruckRun.prj (project) ---

Proj Title=ThunderstruckRun
Current Plan=p01
Default Exp/Contr=0.3,0.1
SI Units
Geom File=g01
Flow File=f01
Plan File=p01
Y Axis Title=Elevation
X Axis Title(PF)=Main Channel Distance
X Axis Title(XS)=Station
BEGIN DESCRIPTION:
September 2018
Tucker County ABFE Study
US Army Corps of Engineers, Pittsburgh District
NAD 1983 UTM 17N (meters)
END DESCRIPTION:
DSS Export Rating Curves= 0
DSS Export Rating Curve Sorted= 0
DSS Export Volume Flow Curves= 0
DXF OffsetX= 0
DXF OffsetY= 0
DXF ScaleX= 1
DXF ScaleY= 10

--- ThunderstruckRun.p01 (plan) ---

Plan Title=ThunderstruckRun_plan
Program Version=5.05
Short Identifier=Plan1_subcritical
Geom File=g01
Flow File=f01
Subcritical Flow
K Sum by GR= 0
Std Step Tol= 0.003
Critical Tol= 0.003
Num of Std Step Trials= 20
Max Error Tol= 0.1
Flow Tol Ratio= 0.001
Split Flow NTrial= 30
Split Flow Tol= 0.006
Split Flow Ratio= 0.02
Log Output Level= 0
Friction Slope Method= 1
Unsteady Friction Slope Method= 2
Unsteady Bridges Friction Slope Method= 1
Parabolic Critical Depth
Global Vel Dist= 0 , 0 , 0
Global Log Level= 0
CheckData=True
Encroach Param=-1 ,0,0, 0
Computation Interval=1MIN
Output Interval=1HOUR
Instantaneous Interval=1HOUR
Mapping Interval=1HOUR
Computation Time Step Use Courant=        0
Computation Time Step Use Time Series=    0
Computation Time Step Count To Double=0
Computation Time Step Max Doubling=0
Computation Time Step Max Halving=0
Computation Time Step Residence Courant=0
Run HTab= 0
Run UNet= 0
Run Sediment= 0
Run PostProcess= 0
Run WQNet= 0
Run RASMapper=-1
UNET Theta= 1
UNET Theta Warmup= 1
UNET ZTol= 0.006
UNET ZSATol= 0.006
UNET MxIter= 20
UNET Max Iter WO Improvement= 0
UNET MaxInSteps= 0
UNET DtIC= 0
UNET DtMin= 0
UNET MaxCRTS= 20
UNET WFStab= 2
UNET SFStab= 1
UNET WFX= 1
UNET SFX= 1
UNET 1D Methodology=Finite Difference
UNET DSS MLevel= 4
UNET Pardiso=0
UNET DZMax Abort= 30
UNET Use Existing IB Tables=-1
UNET Froude Reduction=False
UNET Froude Limit= 0.8
UNET Froude Power= 4
UNET D1 Cores= 0
UNET D2 Coriolis=0
UNET D2 Cores= 0
UNET D2 Theta= 1
UNET D2 Theta Warmup= 1
UNET D2 Z Tol= 0.003
UNET D2 Volume Tol= 0.003
UNET D2 Max Iterations= 20
UNET D2 Equation= 0
UNET D2 RampUpFraction=0.1
UNET D2 TimeSlices= 1
UNET D2 BCVolumeCheck=0
UNET D1D2 MaxIter= 0
UNET D1D2 ZTol=0.003
UNET D1D2 QTol=0.1
UNET D1D2 MinQTol=0.03
Write IC File= 0
Write IC File at Fixed DateTime=0
Write IC File at Sim End=0
Echo Input=False
Echo Parameters=False
Echo Output=False
Write Detailed= 0
HDF Write Warmup=0
HDF Write Time Slices=0
HDF Flush=0
HDF Face Node Velocities=0
HDF Compression= 1
HDF Chunk Size= 1
HDF Spatial Parts= 1
HDF Use Max Rows=0
HDF Fixed Rows= 1
Calibration Method= 0
Calibration Iterations= 20
Calibration Max Change=0.05
Calibration Tolerance=0.2
Calibration Maximum=1.5
Calibration Minimum=0.5
Calibration Optimization Method= 1
WQ AD Non Conservative
WQ ULTIMATE=-1
WQ Max Comp Step=1HOUR
WQ Output Interval=15MIN
WQ Output Selected Increments= 0
WQ Output face flow=0
WQ Output face velocity=0
WQ Output face area=0
WQ Output face dispersion=0
WQ Output cell volume=0
WQ Output cell surface area=0
WQ Output cell continuity=0
WQ Output cumulative cell continuity=0
WQ Output face conc=0
WQ Output face dconc_dx=0
WQ Output face courant=0
WQ Output face peclet=0
WQ Output face adv mass=0
WQ Output face disp mass=0
WQ Output cell mass=0
WQ Output cell source sink temp=0
WQ Output nsm pathways=0
WQ Output nsm derived pathways=0
WQ Output MaxMinRange=-1
WQ Daily Max Min Mean=-1
WQ Daily Range=0
WQ Daily Time=0
WQ Create Restart=0
WQ Fixed Restart=0
WQ System Summary=0
WQ Write To DSS=0
WQ Use Fixed Temperature=0
Sorting and Armoring Iterations= 10
XS Update Threshold= 0.02
Bed Roughness Predictor= 0
Hydraulics Update Threshold= 0.02
Energy Slope Method= 1
Volume Change Method= 1
Sediment Retention Method= 0
XS Weighting Method= 0
Number of US Weighted Cross Sections= 1
Number of DS Weighted Cross Sections= 1
Upstream XS Weight=0
Main XS Weight=1
Downstream XS Weight=0
Number of DS XS's Weighted with US Boundary= 1
Upstream Boundary Weight= 1
Weight of XSs Associated with US Boundary= 0
Number of US XS's Weighted with DS Boundary= 1
Downstream Boundary Weight= 0.5
Weight of XSs Associated with DS Boundary= 0.5
Percentile Method= 0
Sediment Output Level= 4
Mass or Volume Output= 0
Output Increment Type= 1
Profile and TS Output Increment= 1
XS Output Flag= 0
XS Output Increment= 10
Write Gradation File= 0
Read Gradation Hotstart= 0
Write HDF5 File= 1
Write Binary Output= 1
Write DSS Sediment File= 0
SV Curve= 0
Specific Gage Flag= 0

--- ThunderstruckRun.f01 (steady flow) ---

Flow Title=ThunderstruckRun_flow
Program Version=5.05
Number of Profiles= 1
Profile Names=PF 1
River Rch & RM=UnnamedTrib(Hrs),1               ,3382.673
   14.37
River Rch & RM=UnnamedTrib(Hrs),1               ,2742.593
   16.71
River Rch & RM=UnnamedTrib(Hrs),1               ,2468.273
   20.87
River Rch & RM=UnnamedTrib(Hrs),1               ,2193.953
    21.1
River Rch & RM=UnnamedTrib(Hrs),1               ,1462.433
   24.15
River Rch & RM=UnnamedTrib(Hrs),1               ,1188.127
   25.94
River Rch & RM=UnnamedTrib(Hrs),1               ,548.033
   28.52
Boundary for River Rch & Prof#=UnnamedTrib(Hrs),1               , 1
Up Type= 2
Dn Type= 1
Dn Known WS=560
DSS Import GetInterval= 0
DSS Import GetPeak= 0
DSS Import FillOption= 0

--- ThunderstruckRun.g01 (geometry) ---

Geom Title=ThunderstruckRun_geometry
Program Version=5.05

River Reach=UnnamedTrib(Hrs),1
Reach XY= 30
     621142.1775     4343951.471     621249.0607    4343802.9211
      621366.139    4343587.4175   621408.4731464343542.70408613
     621526.4974    4343316.4221621600.0997076674343231.80594307
     621703.0866    4343157.2042     621755.4742    4343082.9884
     621786.3329    4342976.9592  621857.0589646 4342855.0846292
     621891.6026     4342822.241      621952.466    4342698.3445
   622032.0795464342641.45230767     622051.9404    4342596.8155
     622144.6289    4342515.4199     622149.9687    4342454.2048
     622236.8845    4342416.6339622287.627427733 4342318.4540124
622266.7364003334342220.43304307622303.726807667 4342212.4682646
     622317.8472    4342128.1052622364.6403445334342072.83068613
622363.135007999 4342001.2195664     622430.9027    4341957.7159
     622470.6444    4341897.1235622471.8575616664341805.46712627
     622586.3051    4341510.4595      622764.834    4341356.6872
     622792.2184    4341272.5496     622860.5267    4341200.4847

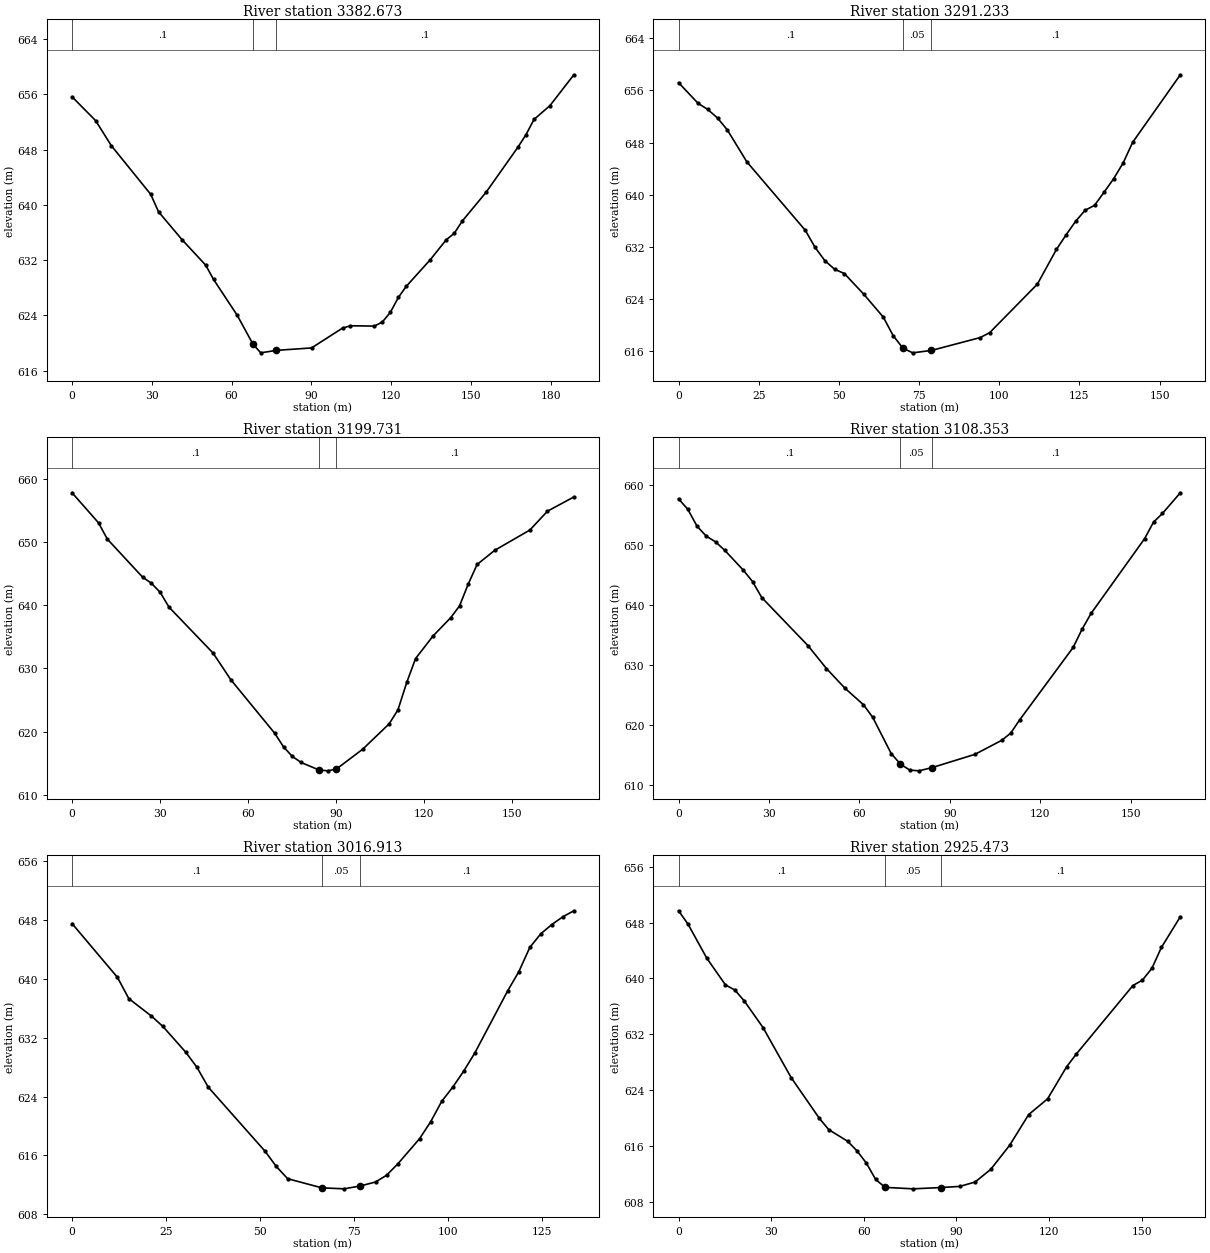
Type RM Length L Ch R = 1 ,3382.673,89.96,91.44,92.43
XS GIS Cut Line= 4
     621251.2015    4343934.0556     621176.5808    4343915.5681
     621162.8067    4343907.7559     621100.0328    4343835.1098
#Sta/Elev= 30
       0  655.65    8.87   652.2   14.78  648.57   29.57  641.54   32.52  639.01
    41.4  634.95   50.27  631.28   53.22  629.21   62.09  624.04   68.01  619.86
   70.96  618.59   76.88  618.95   90.07   619.3  101.71  622.17  104.71  622.51
  113.71  622.46  116.71  623.06  119.71  624.45  122.72  626.61  125.72  628.23
  134.72  632.07  140.72  634.96  143.72  635.88  146.72  637.65  155.72  641.84
  167.72  648.38  170.72  650.17  173.72  652.37  179.72  654.37  188.72  658.84
#Mann= 3 , 0 , 0
       0      .1       0   68.01     .05       0   76.88      .1       0
Bank Sta=68.01,76.88
XS Rating Curve= 0 ,0
Exp/Cntr=0.3,0.1

Type RM Length L Ch R = 1 ,3291.233,93.04,91.5,90.39
XS GIS Cut Line= 3
     621280.9962    4343886.7181      621215.385    4343832.4191
     621162.7392    4343784.3097
#Sta/Elev= 30
       0  657.21    6.08  654.04    9.12  653.09   12.17  651.78   15.21  649.96
   21.29  645.07   39.54  634.56   42.58  631.94   45.62  629.92   48.67  628.59
   51.71  627.94   57.79  624.75   63.87  621.25   66.92  618.42   69.96  616.51
      73  615.78   78.88  616.15   94.08  618.12   97.05  618.88  111.91  626.32
  117.85  631.64  120.82  633.84   123.8  635.93  126.77  637.63  129.74   638.4
  132.71  640.41  135.68  642.47  138.65  644.89  141.62  648.06  156.48  658.41
#Mann= 3 , 0 , 0
       0      .1       0   69.96     .05       0   78.88      .1       0
Bank Sta=69.96,78.88
XS Rating Curve= 0 ,0
Exp/Cntr=0.3,0.1

Type RM Length L Ch R = 1 ,3199.731,90.81,91.38,91.89
XS GIS Cut Line= 3
      621344.118    4343797.5471     621276.7053    4343764.3381
     621192.3461    4343718.5077
#Sta/Elev= 30
       0  657.75    9.02     653   12.02  650.43   24.05  644.41   27.05  643.45
   30.06     642   33.07  639.66    48.1   632.4   54.11  628.21   69.14  619.71
   72.14  617.56   75.15  616.05   78.15   615.1   84.15  613.93   87.15  613.78
   90.15  614.06   99.15  617.21  108.15  621.21  111.15  623.42  114.15  627.76
  117.15  631.53  123.15  635.12  129.15     638  132.15  639.86  135.15  643.34
  138.15  646.41  144.15  648.65  156.15  651.86  162.15  654.84  171.15  657.09
#Mann= 3 , 0 , 0
       0      .1       0   84.15     .05       0   90.15      .1       0
Bank Sta=84.15,90.15
XS Rating Curve= 0 ,0
Exp/Cntr=0.3,0.1

Type RM Length L Ch R = 1 ,3108.353,95.64,91.44,90.8
XS GIS Cut Line= 4
         621388.    4343722.5726     621318.4596    4343683.5956
      621307.827    4343676.7203     621243.1462      4343640.72
#Sta/Elev= 30
       0  657.62    3.07  655.88    6.13  653.06     9.2   651.4   12.26  650.45
   15.33  649.04   21.46  645.74   24.53  643.84   27.59  641.17   42.93  633.15
   49.06  629.33   55.19  626.05   61.32   623.3   64.39  621.21   70.52  615.16
   73.59  613.41   76.65  612.41   79.72  612.28   84.08  612.82    98.3  615.03
  107.19  617.37  110.15  618.56  113.11  620.76  130.87  632.85  133.83  635.89
   136.8  638.51  154.56  650.98  157.52  653.74  160.48  655.18  166.41  658.63
#Mann= 3 , 0 , 0
       0      .1       0   73.59     .05       0   84.08      .1       0
Bank Sta=73.59,84.08
XS Rating Curve= 0 ,0
Exp/Cntr=0.3,0.1

Type RM Length L Ch R = 1 ,3016.913,79.92,91.44,96.18
XS GIS Cut Line= 5
     621427.1063      4343631.35     621367.3543    4343602.4196
      621361.423    4343602.3631     621353.8536    4343598.7298
     621308.8813    4343571.1987
#Sta/Elev= 30
       0  647.53   12.07  640.21   15.09  637.32   21.12  634.94   24.14  633.54
   30.18  630.06   33.19  627.99   36.21  625.28    51.3  616.57   54.32  614.48
   57.33  612.82   66.39  611.58   72.32  611.44   76.53  611.82   80.72  612.37
   83.64  613.29   86.57   614.8   92.43  618.27   95.36  620.56   98.29  623.33
  101.22  625.26  104.15  627.45  107.08   629.9  115.87   638.4   118.8  640.97
  121.73  644.28  124.66  646.14  127.59   647.4  130.52  648.45  133.45  649.27
#Mann= 3 , 0 , 0
       0      .1       0   66.39     .05       0   76.53      .1       0
Bank Sta=66.39,76.53
XS Rating Curve= 0 ,0
Exp/Cntr=0.3,0.1

Type RM Length L Ch R = 1 ,2925.473,97.45,91.44,91.06
XS GIS Cut Line= 5
     621462.0894    4343599.7757     621408.1498     4343530.003
     621405.4366    4343524.7756     621402.9889    4343521.6526
     621368.4267    4343467.2192
#Sta/Elev= 30
       0  649.69    3.04   647.8    9.12  642.92   15.21  639.06   18.25  638.33
   21.29  636.77   27.37  632.95   36.49  625.77   45.62  619.94   48.66  618.32
   54.74  616.67   57.78   615.3   60.82  613.54   63.86  611.18    66.9  610.05
   76.03  609.84   85.15  610.03   91.14  610.19   96.06  610.82  101.12  612.63
  107.26  616.09   113.4  620.48  119.54  622.74  125.68  627.32  128.75  629.11
  147.18  638.98  150.25  639.75  153.32  641.44  156.39  644.43  162.53  648.84
#Mann= 3 , 0 , 0
       0      .1       0    66.9     .05       0   85.15      .1       0
Bank Sta=66.9,85.15
XS Rating Curve= 0 ,0
Exp/Cntr=0.3,0.1

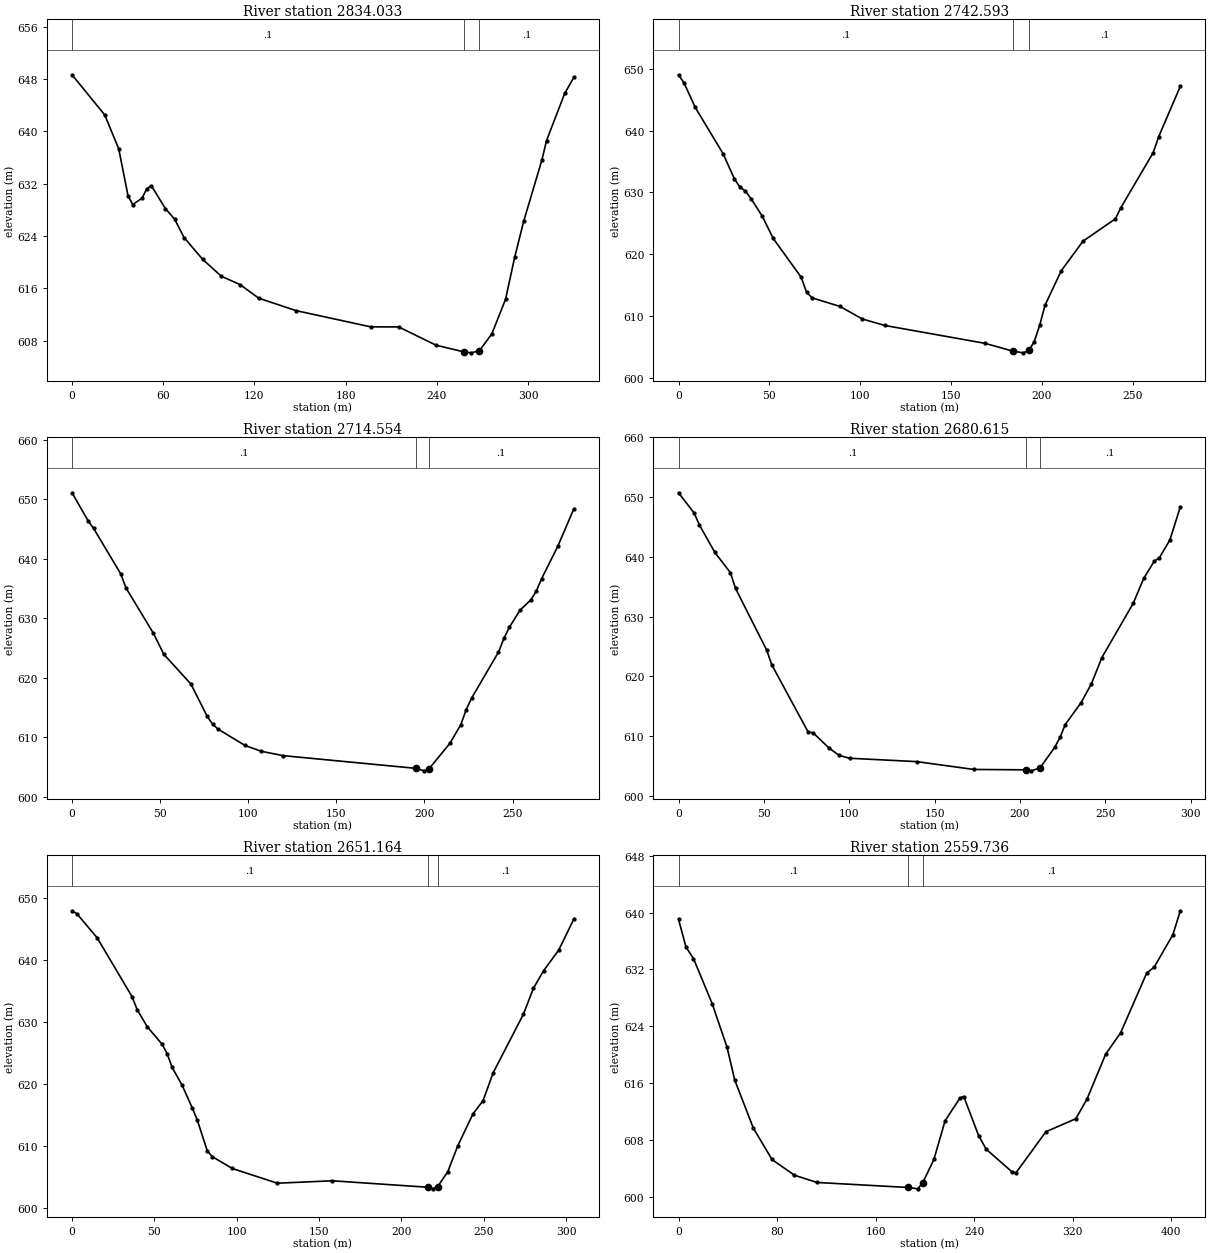
Type RM Length L Ch R = 1 ,2834.033,91.93,91.44,88.96
XS GIS Cut Line= 5
     621655.7647    4343622.7945     621460.6618     4343454.156
     621455.4589    4343451.7195     621450.3684    4343447.5453
     621401.7642    4343412.4503
#Sta/Elev= 30
       0  648.64   21.49   642.5    30.7  637.33   36.84  630.13   39.91  628.82
   46.05  629.78   49.12  631.23   52.19  631.69    61.4   628.2   67.54  626.56
   73.68  623.78   85.96  620.43   98.24  617.86  110.52  616.59   122.8  614.51
  147.36  612.61  196.48  610.13   214.9  610.12  239.46  607.33  257.88   606.3
  262.73  606.16  268.02  606.48  276.21  609.07   285.2  614.33  291.19  620.73
  297.19   626.3  309.18  635.65  312.18  638.59  324.17  645.81  330.16  648.25
#Mann= 3 , 0 , 0
       0      .1       0  257.88     .05       0  268.02      .1       0
Bank Sta=257.88,268.02
XS Rating Curve= 0 ,0
Exp/Cntr=0.3,0.1

Type RM Length L Ch R = 1 ,2742.593,27.2,28.04,28.58
XS GIS Cut Line= 4
     621660.2627    4343461.5086     621496.4246    4343371.2207
     621493.8799    4343370.0826     621418.9622       4343327.1
#Sta/Elev= 30
       0  649.04    3.07  647.69     9.2  643.75   24.53  636.25   30.67  632.23
   33.73  630.87    36.8  630.21   39.87  628.99      46  626.18   52.13  622.53
   67.47  616.26   70.53  613.79    73.6   612.9   88.93  611.51   101.2  609.48
  113.47  608.44  168.67  605.54     184  604.28  189.86     604  192.84  604.38
  195.81  605.82  198.79  608.44  201.77  611.73  210.71  617.31  222.62  622.08
  240.49  625.71  243.47   627.5  261.34  636.45  264.32  639.01  276.23  647.18
#Mann= 3 , 0 , 0
       0      .1       0     184     .05       0  192.84      .1       0
Bank Sta=184,192.84
XS Rating Curve= 0 ,0
Exp/Cntr=0.3,0.1

Type RM Length L Ch R = 1 ,2714.554,34.29,33.94,30.7
XS GIS Cut Line= 5
     621683.2758    4343442.4036     621516.4557    4343351.2544
     621512.2223    4343348.7409     621506.4015    4343344.3752
      621435.493    4343302.2403
#Sta/Elev= 30
       0  651.06     9.2  646.29   12.26  645.06   27.59  637.45   30.66  635.04
   45.99  627.54   52.12  623.91   67.45  618.92   76.65  613.52   79.72   612.2
   82.78  611.36   98.11  608.61  107.31  607.63  119.58   606.9  195.02  604.76
  199.87  604.34   202.3  604.57  214.52     609  220.63   612.1  223.68  614.63
  226.74  616.56  242.01  624.29  245.07  626.59  248.12  628.43  254.23  631.34
  260.34  633.06   263.4  634.49  266.45  636.61  275.61  642.04  284.78  648.37
#Mann= 3 , 0 , 0
       0      .1       0  195.02     .05       0   202.3      .1       0
Bank Sta=195.02,202.3
XS Rating Curve= 0 ,0
Exp/Cntr=0.3,0.1

Type RM Length L Ch R = 1 ,2680.615,27.7,29.45,31.98
XS GIS Cut Line= 5
     621710.3383    4343417.0697     621536.7052    4343323.4731
      621532.075    4343318.8429     621521.7033    4343317.7316
     621451.8531    4343279.4199
#Sta/Elev= 30
       0  650.72     9.1  647.35   12.14  645.38   21.24  640.75   30.35  637.37
   33.38  634.72   51.59  624.43   54.62  621.94   75.87  610.73    78.9  610.55
   88.01  608.06   94.07  606.79  100.14  606.32  139.59  605.75  172.98  604.44
   203.8  604.38  206.41  604.21  211.62  604.67  220.36  608.15  223.42  609.79
  226.49  611.95  235.68  615.58  241.81  618.76  247.94  623.15  266.32  632.24
  272.45  636.39  278.58  639.25  281.64  639.86  287.77  642.81   293.9  648.36
#Mann= 3 , 0 , 0
       0      .1       0   203.8     .05       0  211.62      .1       0
Bank Sta=203.8,211.62
XS Rating Curve= 0 ,0
Exp/Cntr=0.3,0.1

Type RM Length L Ch R = 1 ,2651.164,85.52,91.43,94.59
XS GIS Cut Line= 3
     621737.5212    4343398.0084     621549.2505    4343298.8262
      621475.054    4343244.5498
#Sta/Elev= 30
       0  647.99    3.04  647.48    15.2  643.64   36.48  634.09   39.52  632.03
    45.6  629.28   54.72  626.42   57.76  624.89    60.8  622.68   66.88  619.78
   72.96  616.17      76  614.22   82.08  609.24   85.12  608.28   97.28  606.37
  124.64  603.99  158.08  604.38  215.86  603.34  218.93  603.08  221.99  603.44
  228.12  605.82  234.25  610.04  243.44  615.17  249.57  617.32   255.7  621.81
  274.08  631.28  280.21  635.49  286.34  638.31  295.53  641.64  304.73  646.66
#Mann= 3 , 0 , 0
       0      .1       0  215.86     .05       0  221.99      .1       0
Bank Sta=215.86,221.99
XS Rating Curve= 0 ,0
Exp/Cntr=0.3,0.1

Type RM Length L Ch R = 1 ,2559.736,88.92,91.46,93.85
XS GIS Cut Line= 4
     621725.8795    4343378.9584     621611.1119    4343245.4236
     621606.3251    4343233.1809      621484.579    4343051.9327
#Sta/Elev= 30
       0  639.05    6.07  635.14   12.14  633.54   27.32  627.19   39.47  621.02
   45.54  616.49   60.72  609.69    75.9  605.26   94.11  603.05  112.33  602.03
  186.59  601.32  194.34  601.13  198.34  601.98  207.42  605.27  216.52  610.72
  228.65  613.93  231.68  614.11  243.81  608.59  249.87  606.71   271.1  603.48
  274.13   603.4  298.39  609.17  322.65  610.99  331.75  613.76  346.91  620.08
  359.04  623.08  380.27   631.5  386.34  632.33   401.5  636.89  407.56  640.26
#Mann= 3 , 0 , 0
       0      .1       0  186.59     .05       0  198.34      .1       0
Bank Sta=186.59,198.34
XS Rating Curve= 0 ,0
Exp/Cntr=0.3,0.1

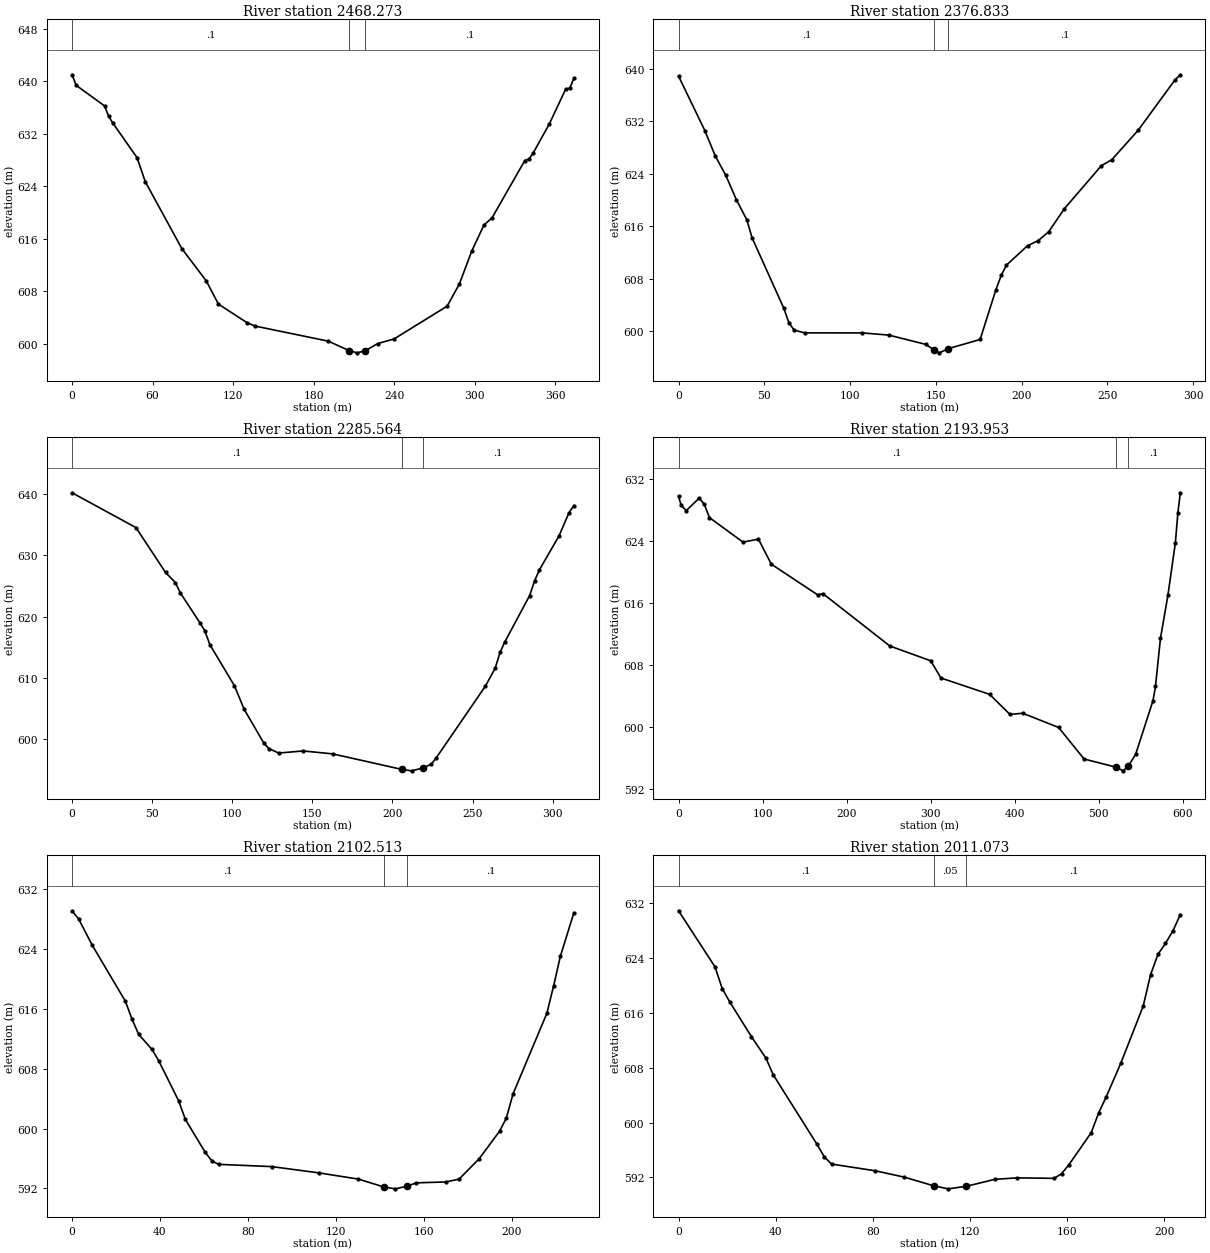
Type RM Length L Ch R = 1 ,2468.273,101.18,91.44,84.85
XS GIS Cut Line= 4
     621811.6046    4343329.2166     621682.0805     4343201.726
     621671.2232    4343166.5993     621613.6959    4343022.2994
#Sta/Elev= 30
       0  640.96    3.03  639.36   24.23  636.21   27.26  634.64   30.29  633.63
   48.46  628.31   54.52  624.68   81.78  614.47   99.96  609.56  109.05  606.01
  130.25   603.2  136.31  602.67  190.93  600.37  206.25  598.94  212.38  598.59
  218.51  598.91  227.65     600  239.83   600.7  279.43   605.7  288.57  609.09
   297.7  614.06  306.84  618.06  312.93  619.17   337.3  627.89  340.35  628.11
  343.39  628.98  355.58  633.47  367.76  638.78  370.81  638.92  373.85   640.4
#Mann= 3 , 0 , 0
       0      .1       0  206.25     .05       0  218.51      .1       0
Bank Sta=206.25,218.51
XS Rating Curve= 0 ,0
Exp/Cntr=0.3,0.1

Type RM Length L Ch R = 1 ,2376.833,94.54,91.27,88.07
XS GIS Cut Line= 4
     621859.7236    4343199.3236     621743.0062     4343114.933
     621731.8845    4343107.4733     621625.8315    4343023.6399
#Sta/Elev= 30
       0  638.91   15.32   630.6   21.45   626.7   27.58  623.75   33.71  620.04
   39.84  616.96    42.9  614.21   61.29  603.53   64.35  601.26   67.42  600.12
   73.55  599.71  107.26   599.7  122.58  599.37  144.03  597.96  149.16   597.1
  152.07  596.66  157.42  597.31  175.86   598.7  185.07  606.29  188.15  608.47
  191.22  610.05  203.51  613.01  209.65  613.78   215.8  615.13  225.02  618.67
  246.52  625.22  252.67  626.15  268.03  630.64  289.54  638.34  292.61  639.11
#Mann= 3 , 0 , 0
       0      .1       0  149.16     .05       0  157.42      .1       0
Bank Sta=149.16,157.42
XS Rating Curve= 0 ,0
Exp/Cntr=0.3,0.1

Type RM Length L Ch R = 1 ,2285.564,87.09,91.61,93.31
XS GIS Cut Line= 2
     621981.4322    4343094.5484     621682.9816    4342999.2982
#Sta/Elev= 30
       0  640.23   39.93  634.53   58.36   627.2    64.5  625.55   67.57  623.87
   79.86  618.97   82.93  617.63      86  615.42  101.36  608.69   107.5  604.81
  119.78  599.29  122.86  598.42     129  597.69  144.36  598.03  162.78  597.55
  205.78  595.02  211.93  594.78  218.88  595.23  224.21  595.86  227.28  596.87
     258  608.61  264.14  611.54  267.21  614.15  270.28  615.91  285.64  623.41
  288.71   625.8  291.78  627.64  304.07  633.21  310.21  636.95  313.28  638.13
#Mann= 3 , 0 , 0
       0      .1       0  205.78     .05       0  218.88      .1       0
Bank Sta=205.78,218.88
XS Rating Curve= 0 ,0
Exp/Cntr=0.3,0.1

Type RM Length L Ch R = 1 ,2193.953,93.64,91.44,90.7
XS GIS Cut Line= 5
     622270.8869     4343199.059     622073.2428    4343069.6775
     621834.1914    4342970.7547     621814.2776    4342950.4714
     621756.0178    4342905.0289
#Sta/Elev= 30
       0  629.76    3.07   628.6     9.2   627.9   24.54  629.51   30.68  628.71
   36.81     627    76.7  623.84    95.1  624.23  110.44     621  165.67  617.04
   171.8  617.21  251.44  610.46  300.14  608.55  312.32  606.33  370.15  604.23
   394.5  601.64  409.71  601.79  452.33  599.96  482.76  595.89  520.52  594.85
  529.27  594.37  535.18  594.97  544.05  596.49  564.74  603.42  567.69  605.26
   573.6  611.44  582.47  616.99  591.34  623.75  594.29  627.56  597.25   630.2
#Mann= 3 , 0 , 0
       0      .1       0  520.52     .05       0  535.18      .1       0
Bank Sta=520.52,535.18
XS Rating Curve= 0 ,0
Exp/Cntr=0.3,0.1

Type RM Length L Ch R = 1 ,2102.513,90.16,91.44,85.3
XS GIS Cut Line= 6
     621982.7154    4342936.4198     621859.0711    4342871.9944
     621851.4643    4342870.7376     621846.5695    4342868.2241
     621836.2198    4342858.5875     621778.1745    4342838.3261
#Sta/Elev= 30
       0  629.09    3.03  627.98    9.09  624.53   24.25  617.01   27.28  614.61
   30.31  612.58   36.37  610.57    39.4  609.07   48.49   603.7   51.53  601.23
   60.62   596.8   63.65  595.66   66.68  595.21   90.93  594.91  112.14  594.08
  130.33  593.24  141.99  592.18  147.13  591.94  152.63  592.31  156.65  592.74
  169.93  592.86  176.08  593.23   185.3  595.98  194.53  599.64   197.6  601.38
  200.67  604.63  216.04  615.38  219.12  619.04  222.19     623  228.34  628.82
#Mann= 3 , 0 , 0
       0      .1       0  141.99     .05       0  152.63      .1       0
Bank Sta=141.99,152.63
XS Rating Curve= 0 ,0
Exp/Cntr=0.3,0.1

Type RM Length L Ch R = 1 ,2011.073,92.58,91.44,93.08
XS GIS Cut Line= 5
     622000.5748    4342861.6749     621903.5979    4342801.8289
     621902.4084    4342800.6355     621891.8067    4342796.3083
     621824.6266     4342753.857
#Sta/Elev= 30
       0  630.85   14.99  622.69   17.99  619.51   20.99  617.63   29.99  612.52
   35.99  609.37   38.99  606.95   56.98  596.84   59.98  595.01   62.98  593.95
   80.97  592.97   92.96  592.04  104.96  590.79  110.96  590.34   118.5  590.71
  130.15  591.72  139.32  591.94   154.6  591.87  157.66  592.54  160.71  593.86
  169.88  598.52  172.94  601.41     176   603.7  182.11  608.69  191.28  616.96
  194.33  621.56  197.39  624.53  200.45  626.09   203.5  627.92  206.56  630.29
#Mann= 3 , 0 , 0
       0      .1       0  104.96     .05       0   118.5      .1       0
Bank Sta=104.96,118.5
XS Rating Curve= 0 ,0
Exp/Cntr=0.3,0.1

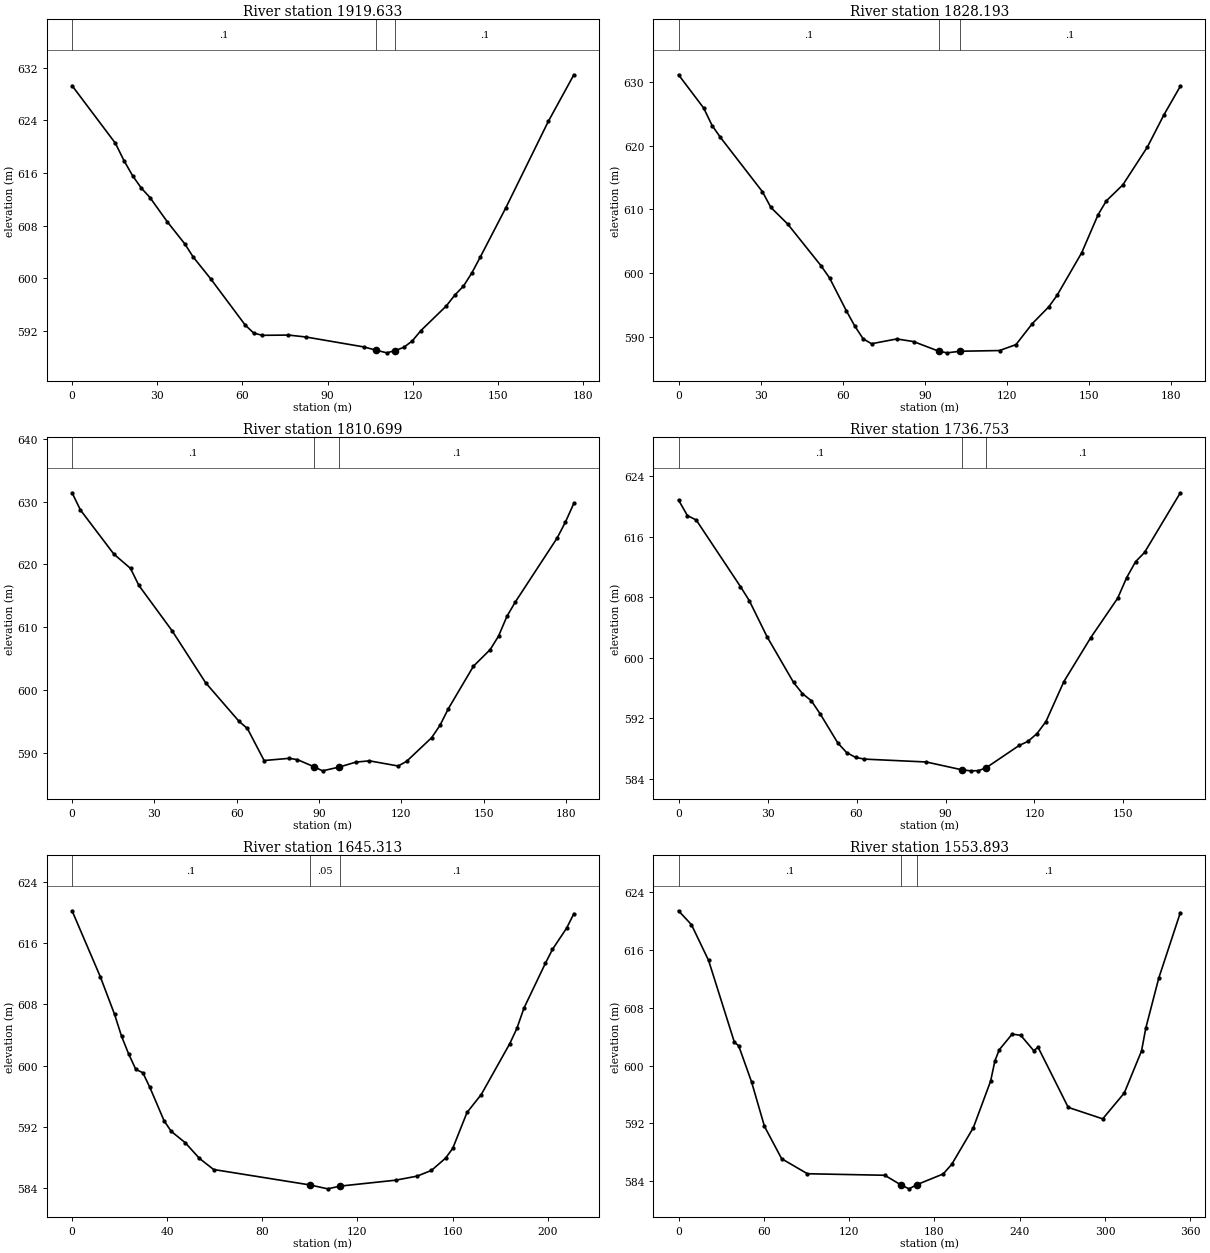
Type RM Length L Ch R = 1 ,1919.633,89.13,91.44,92.4
XS GIS Cut Line= 4
      622031.939    4342776.2915     621950.0235    4342723.2767
     621938.5467     4342716.495     621888.4023    4342673.7652
#Sta/Elev= 30
       0  629.27   15.25  620.53    18.3  617.88   21.34  615.58   24.39  613.72
   27.44  612.28   33.54   608.6   39.64  605.28   42.69  603.24   48.79  599.96
   60.98  592.92   64.03  591.68   67.08  591.35   76.23  591.39   82.33   591.1
  102.91  589.58   107.1  589.09   110.9  588.69   113.9  589.04  116.89  589.53
  119.89  590.51  122.88  592.06  131.87  595.82  134.86  597.47  137.86   598.8
  140.85  600.83  143.85  603.26  152.83  610.73   167.8  623.85  176.79  630.92
#Mann= 3 , 0 , 0
       0      .1       0   107.1     .05       0   113.9      .1       0
Bank Sta=107.1,113.9
XS Rating Curve= 0 ,0
Exp/Cntr=0.3,0.1

Type RM Length L Ch R = 1 ,1828.193,18.43,17.49,15.27
XS GIS Cut Line= 5
      622090.809    4342716.7601     622010.2655    4342660.7125
     622004.0137     4342655.528     622003.0053    4342653.7753
     621945.9493    4342604.9734
#Sta/Elev= 30
       0  631.11     9.2  625.88   12.27  623.14   15.33  621.27   30.66  612.75
   33.73  610.29   39.86  607.69   52.13   601.1    55.2   599.2   61.33  594.05
   64.39  591.67   67.46  589.66   70.53  588.89   79.73  589.64   85.86  589.23
   95.06  587.72   98.13  587.46  102.83  587.71  117.28  587.82  123.29  588.75
  129.29  592.06   135.3  594.69   138.3  596.48  147.31  603.17  153.32  609.16
  156.32  611.32  162.33  613.82  171.34  619.79  177.34  624.81  183.35  629.31
#Mann= 3 , 0 , 0
       0      .1       0   95.06     .05       0  102.83      .1       0
Bank Sta=95.06,102.83
XS Rating Curve= 0 ,0
Exp/Cntr=0.3,0.1

Type RM Length L Ch R = 1 ,1810.699,70.58,73.95,71.82
XS GIS Cut Line= 4
     622103.9994    4342701.8995     622018.2743    4342643.9556
     622007.6909    4342637.6056     621953.9804    4342597.3889
#Sta/Elev= 30
       0  631.41    3.04  628.68   15.22  621.66    21.3  619.38   24.35  616.67
   36.52  609.42   48.69  601.18   60.87  595.04   63.91  593.91      70  588.81
   79.13  589.16   82.17  588.95   88.25  587.81    91.3  587.17   97.38  587.77
  103.47  588.56  108.41  588.76  118.86  587.94  121.91  588.67  131.06  592.44
  134.11  594.41  137.16  597.06  146.31  603.82  152.41  606.46  155.46  608.61
  158.51  611.75  161.56  614.03  176.81  624.21  179.86  626.77  182.91  629.74
#Mann= 3 , 0 , 0
       0      .1       0   88.25     .05       0   97.38      .1       0
Bank Sta=88.25,97.38
XS Rating Curve= 0 ,0
Exp/Cntr=0.3,0.1

Type RM Length L Ch R = 1 ,1736.753,87.98,91.44,95.01
XS GIS Cut Line= 4
     622128.5122     4342660.536     622060.3259    4342589.5221
     622052.8377    4342582.4212     622006.1421    4342544.1191
#Sta/Elev= 30
       0  620.85    2.98   618.8    5.97  618.21   20.88  609.41   23.87  607.54
   29.83  602.79   38.78  596.74   41.77  595.27   44.75  594.33   47.73   592.6
    53.7  588.74   56.68  587.47   59.67  586.84   62.65  586.61   83.53  586.23
   95.47   585.2   98.45  585.06  101.03  585.08  103.61  585.44  114.81  588.41
  117.83  588.96  120.85  589.99  123.87  591.58  129.91  596.86  138.97  602.67
  148.03  607.87  151.05  610.58  154.07   612.7  157.09  613.92  169.16  621.81
#Mann= 3 , 0 , 0
       0      .1       0   95.47     .05       0  103.61      .1       0
Bank Sta=95.47,103.61
XS Rating Curve= 0 ,0
Exp/Cntr=0.3,0.1

Type RM Length L Ch R = 1 ,1645.313,95.05,91.42,75.69
XS GIS Cut Line= 6
     622188.9806    4342613.1866     622137.4889    4342547.6784
     622128.9958     4342530.163     622126.2768    4342526.3327
     622121.5213    4342516.8015     622052.7199    4342454.4362
#Sta/Elev= 30
       0  620.21    11.9  611.59   17.85  606.72   20.83  603.83   23.81  601.53
   26.78  599.54   29.76  599.09   32.73  597.17   38.69  592.83   41.66  591.46
   47.61  589.96   53.56  587.92   59.52  586.47  100.01  584.46  107.51  583.95
  112.83  584.31  136.13  585.08  145.12  585.61  151.11  586.35   157.1  587.96
   160.1  589.24  166.09  593.91  172.08  596.25  184.06  602.88  187.06  604.87
  190.05  607.53  199.04  613.36  202.03  615.18  208.02  617.97  211.02  619.83
#Mann= 3 , 0 , 0
       0      .1       0  100.01     .05       0  112.83      .1       0
Bank Sta=100.01,112.83
XS Rating Curve= 0 ,0
Exp/Cntr=0.3,0.1

Type RM Length L Ch R = 1 ,1553.893,77.16,78.99,75.1
XS GIS Cut Line= 4
      622255.788    4342586.0667     622165.5789    4342464.8637
     622154.6254    4342456.4286     622030.8917    4342314.8682
#Sta/Elev= 30
       0  621.43    9.07  619.51   21.15  614.55   39.28  603.23    42.3  602.74
   51.37  597.73   60.44  591.58   72.52   587.1   90.65  585.02  145.05  584.81
  156.62  583.45  162.15  582.93  167.64  583.51  186.14  584.99  192.21  586.34
  207.37  591.41   219.5  597.85  222.53  600.66  225.56  602.18  234.66  604.36
  240.73  604.18  249.82  602.06  252.86  602.54  274.08  594.21  298.34  592.62
  313.51   596.2  325.64  602.02  328.67  605.21  337.77  612.11  352.93  621.17
#Mann= 3 , 0 , 0
       0      .1       0  156.62     .05       0  167.64      .1       0
Bank Sta=156.62,167.64
XS Rating Curve= 0 ,0
Exp/Cntr=0.3,0.1

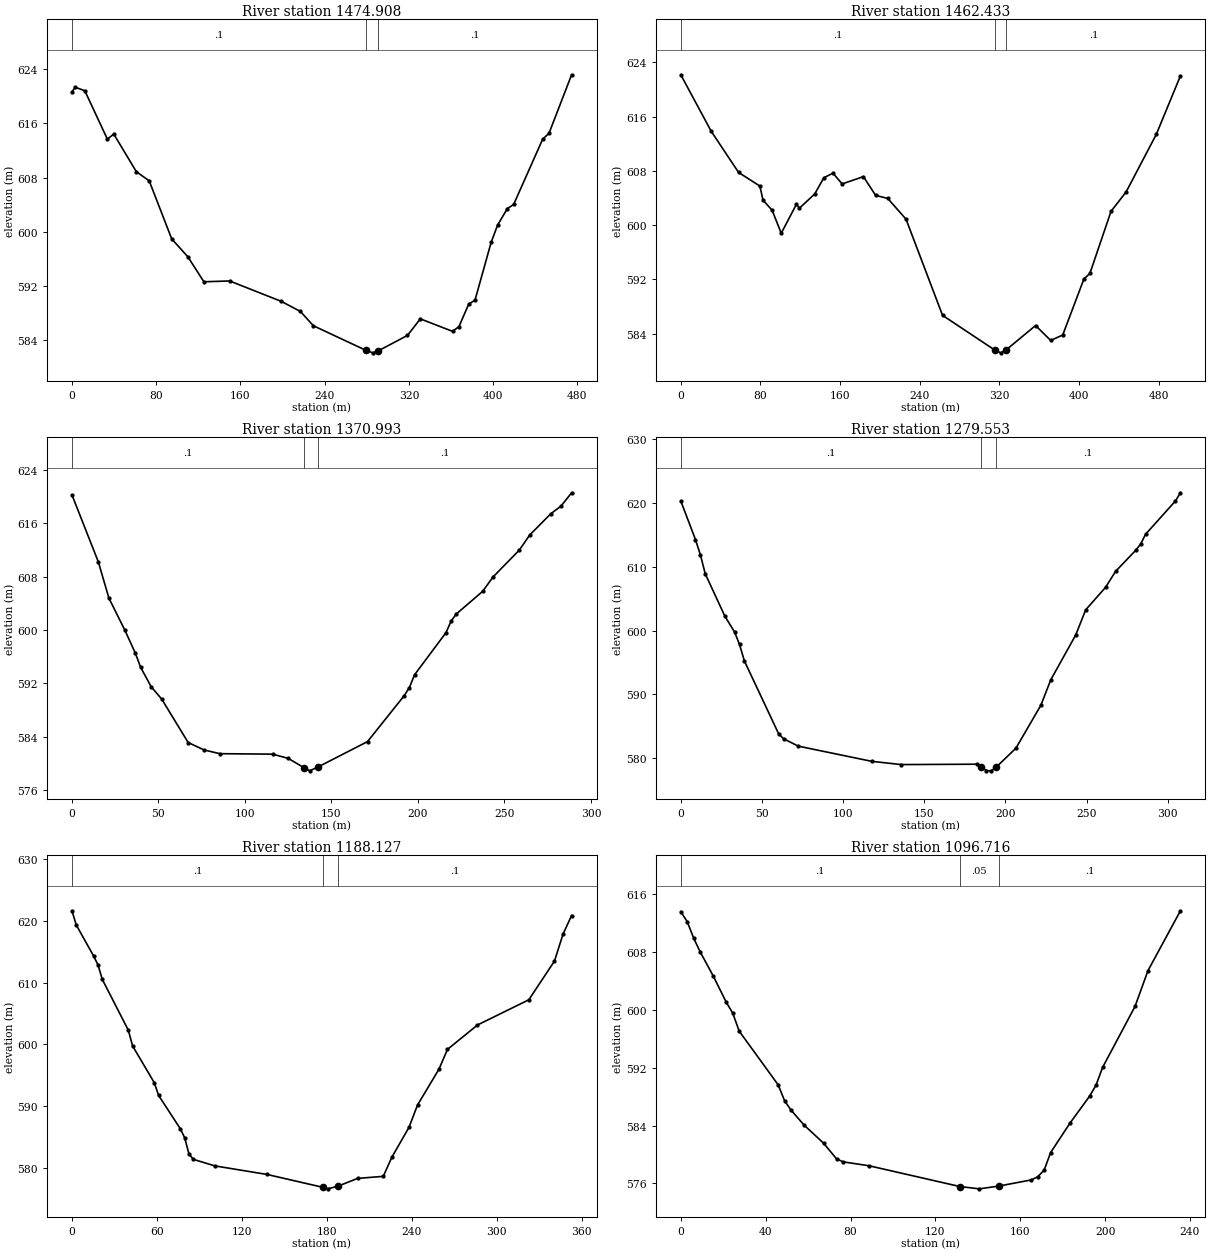
Type RM Length L Ch R = 1 ,1474.908,12,12.47,10.83
XS GIS Cut Line= 4
      622395.368    4342652.9506      622229.668    4342433.3813
     622217.8146    4342422.5862     622103.5144    4342279.1606
#Sta/Elev= 30
       0  620.64    3.06  621.35   12.23  620.82   33.62  613.69   39.73  614.43
   61.13  608.89   73.35  607.54   94.75  598.97  110.03  596.34  125.31  592.65
  149.76  592.77  198.67  589.77     217  588.27  229.23  586.17  279.43  582.52
  285.76  582.17  291.11  582.48  318.62  584.74  330.85  587.18  361.41  585.34
  367.53  586.04   376.7  589.33  382.81  589.96  398.09  598.46  404.21     601
  413.38  603.42  419.49  604.06     447  613.67  453.11  614.57  474.51  623.18
#Mann= 3 , 0 , 0
       0      .1       0  279.43     .05       0  291.11      .1       0
Bank Sta=279.43,291.11
XS Rating Curve= 0 ,0
Exp/Cntr=0.3,0.1

Type RM Length L Ch R = 1 ,1462.433,93.98,91.44,89.21
XS GIS Cut Line= 6
      622452.903    4342648.9054     622238.7099    4342426.5652
     622234.8549    4342421.3713     622228.5049    4342415.0213
     622222.0411    4342410.5314       622116.22    4342277.8265
#Sta/Elev= 30
       0  622.16   30.57  613.82   58.08  607.75   79.47  605.74   82.53  603.68
    91.7  602.18  100.87  598.79  116.16  603.07  119.21  602.49   134.5  604.58
  143.67  606.97  152.84  607.66  162.01  606.06   183.4  607.14  195.63  604.38
  207.86  603.92   226.2  600.86  262.88  586.68   315.2  581.57  321.18  581.15
   326.8  581.59   356.3  585.18  371.45  582.98  383.57  583.78  404.79  592.02
  410.85  592.86  432.07  602.02  447.22  604.88  477.53  613.37  501.78     622
#Mann= 3 , 0 , 0
       0      .1       0   315.2     .05       0   326.8      .1       0
Bank Sta=315.2,326.8
XS Rating Curve= 0 ,0
Exp/Cntr=0.3,0.1

Type RM Length L Ch R = 1 ,1370.993,93,91.44,80.12
XS GIS Cut Line= 4
     622396.2556    4342410.8064     622284.0321    4342348.8178
     622271.4666    4342335.3284     622151.2509    4342259.4644
#Sta/Elev= 30
       0  620.24   15.26   610.2   21.37  604.77   30.53  600.01   36.63  596.55
   39.68  594.43   45.79  591.51   51.89  589.66   67.16  583.16   76.31  582.05
   85.47  581.49     116  581.42  125.15  580.77  134.35  579.35  137.42  578.92
  142.24   579.5  170.84   583.3  192.01  590.17  195.03   591.4  198.06  593.32
   216.2  599.62  219.23  601.39  222.25  602.43  237.38   605.8  243.43  607.97
  258.55  611.97   264.6  614.24  276.69   617.4  282.74  618.59  288.79  620.56
#Mann= 3 , 0 , 0
       0      .1       0  134.35     .05       0  142.24      .1       0
Bank Sta=134.35,142.24
XS Rating Curve= 0 ,0
Exp/Cntr=0.3,0.1

Type RM Length L Ch R = 1 ,1279.553,99.51,91.43,80.03
XS GIS Cut Line= 6
     622439.6473    4342335.1354     622324.8291    4342266.9914
     622320.9077     4342269.342     622305.1772    4342261.9412
      622266.683    4342265.7577     622153.9497    4342251.2623
#Sta/Elev= 30
       0  620.31    9.05  614.25   12.06  611.88   15.08  608.89   27.14  602.26
   33.17  599.76   36.19  597.82    39.2  595.23   60.31  583.81   63.32  583.05
   72.37  581.89   117.6  579.51  135.82     579  182.27  579.06  185.25  578.65
  188.23  578.06   191.2  578.02  194.18  578.56  206.46  581.56  221.82  588.28
  227.97  592.29  243.33  599.31  249.47  603.25  261.76  606.79   267.9  609.28
  280.19  612.55  283.26  613.52  286.33  615.08  304.77  620.31  307.84  621.59
#Mann= 3 , 0 , 0
       0      .1       0  185.25     .05       0  194.18      .1       0
Bank Sta=185.25,194.18
XS Rating Curve= 0 ,0
Exp/Cntr=0.3,0.1

Type RM Length L Ch R = 1 ,1188.127,79.9,91.41,96.12
XS GIS Cut Line= 3
     622485.7379    4342182.2059     622302.2188    4342182.1625
     622134.1059    4342201.2559
#Sta/Elev= 30
       0  621.62    3.06  619.31   15.29  614.31   18.35  612.88   21.41  610.52
   39.76  602.31   42.82  599.75   58.11  593.81   61.17  591.75   76.47  586.37
   79.52  584.93   82.58   582.3   85.64  581.41  100.94  580.35  137.64  578.97
   177.4  576.87  180.46  576.64  187.67  577.06  201.65  578.33  219.77  578.66
  225.82  581.76   237.9  586.58  243.95   590.2  259.05  595.99  265.09   599.2
  286.24  603.14   322.5  607.22  340.63  613.49  346.67  617.85  352.71  620.85
#Mann= 3 , 0 , 0
       0      .1       0   177.4     .05       0  187.67      .1       0
Bank Sta=177.4,187.67
XS Rating Curve= 0 ,0
Exp/Cntr=0.3,0.1

Type RM Length L Ch R = 1 ,1096.716,88.39,91.48,93.94
XS GIS Cut Line= 2
      622471.185    4342176.7536     622259.3599    4342073.7794
#Sta/Elev= 30
       0  613.56    3.06  612.16    6.12  609.86    9.18  607.98   15.29  604.67
   21.41  601.05   24.47  599.55   27.53  597.05   45.88  589.64   48.94  587.43
      52  586.12   58.12  584.07   67.29  581.57   73.41  579.41   76.47  578.99
   88.71  578.45  131.53  575.58  140.71  575.26  149.88  575.64  165.18  576.49
  168.23  576.92  171.29  577.85  174.35  580.28  183.53  584.37   192.7  588.06
  195.76   589.6  198.82  592.03  214.12  600.46  220.23  605.41  235.53  613.68
#Mann= 3 , 0 , 0
       0      .1       0  131.53     .05       0  149.88      .1       0
Bank Sta=131.53,149.88
XS Rating Curve= 0 ,0
Exp/Cntr=0.3,0.1