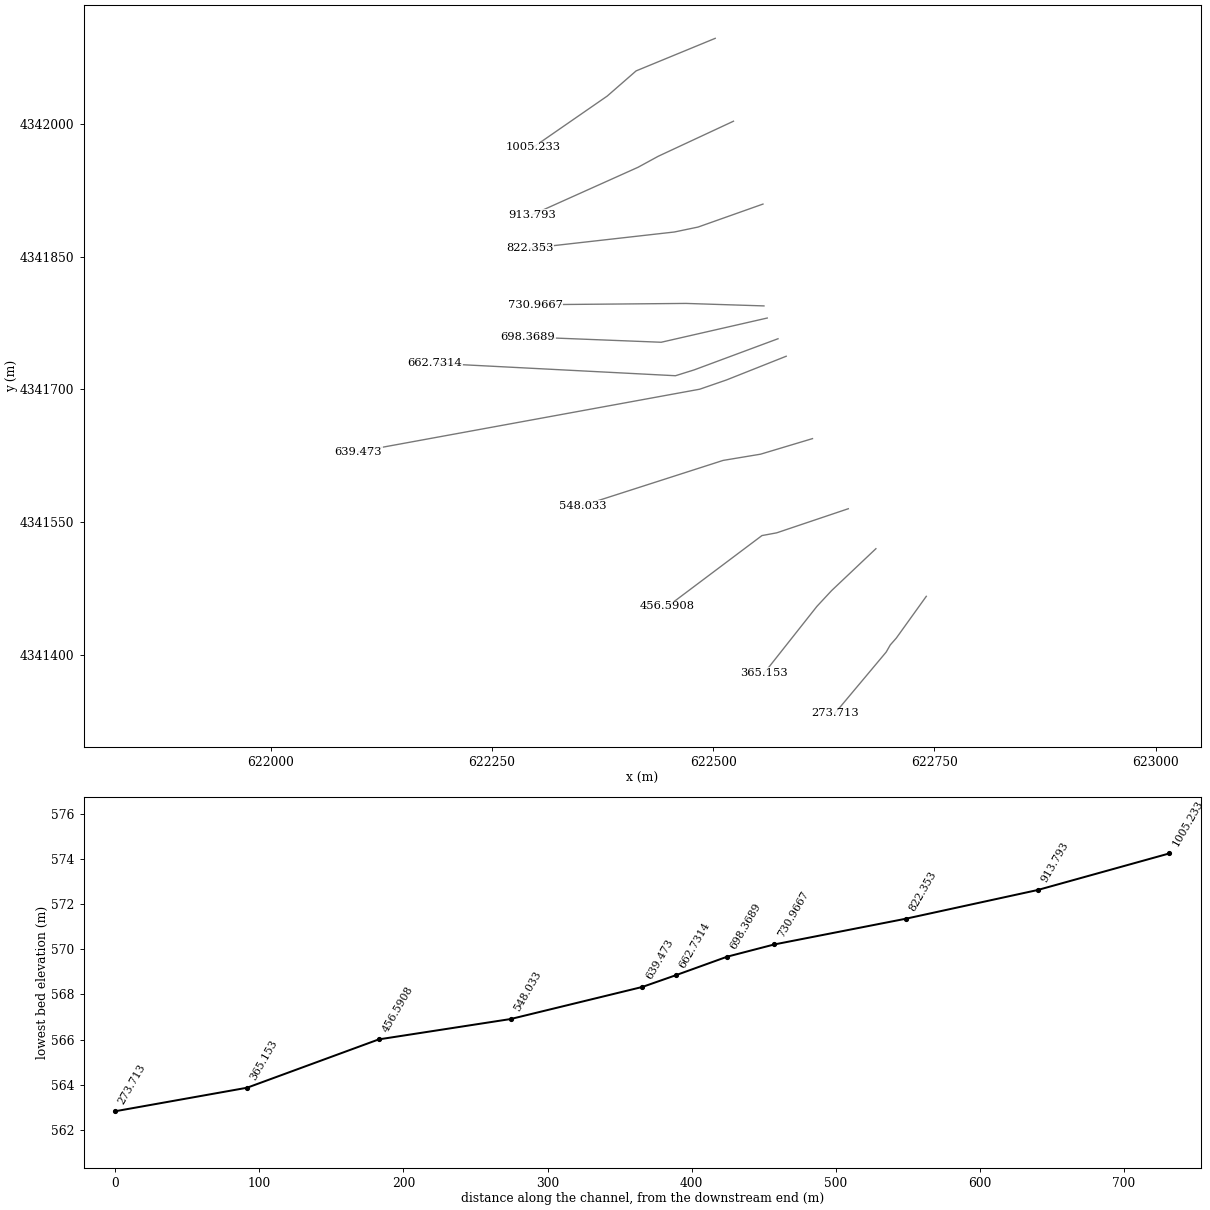
HEC-RAS study ThunderstruckRun.prj: ThunderstruckRun

--- ThunderstruckRun.g01 (geometry) --- (continued)

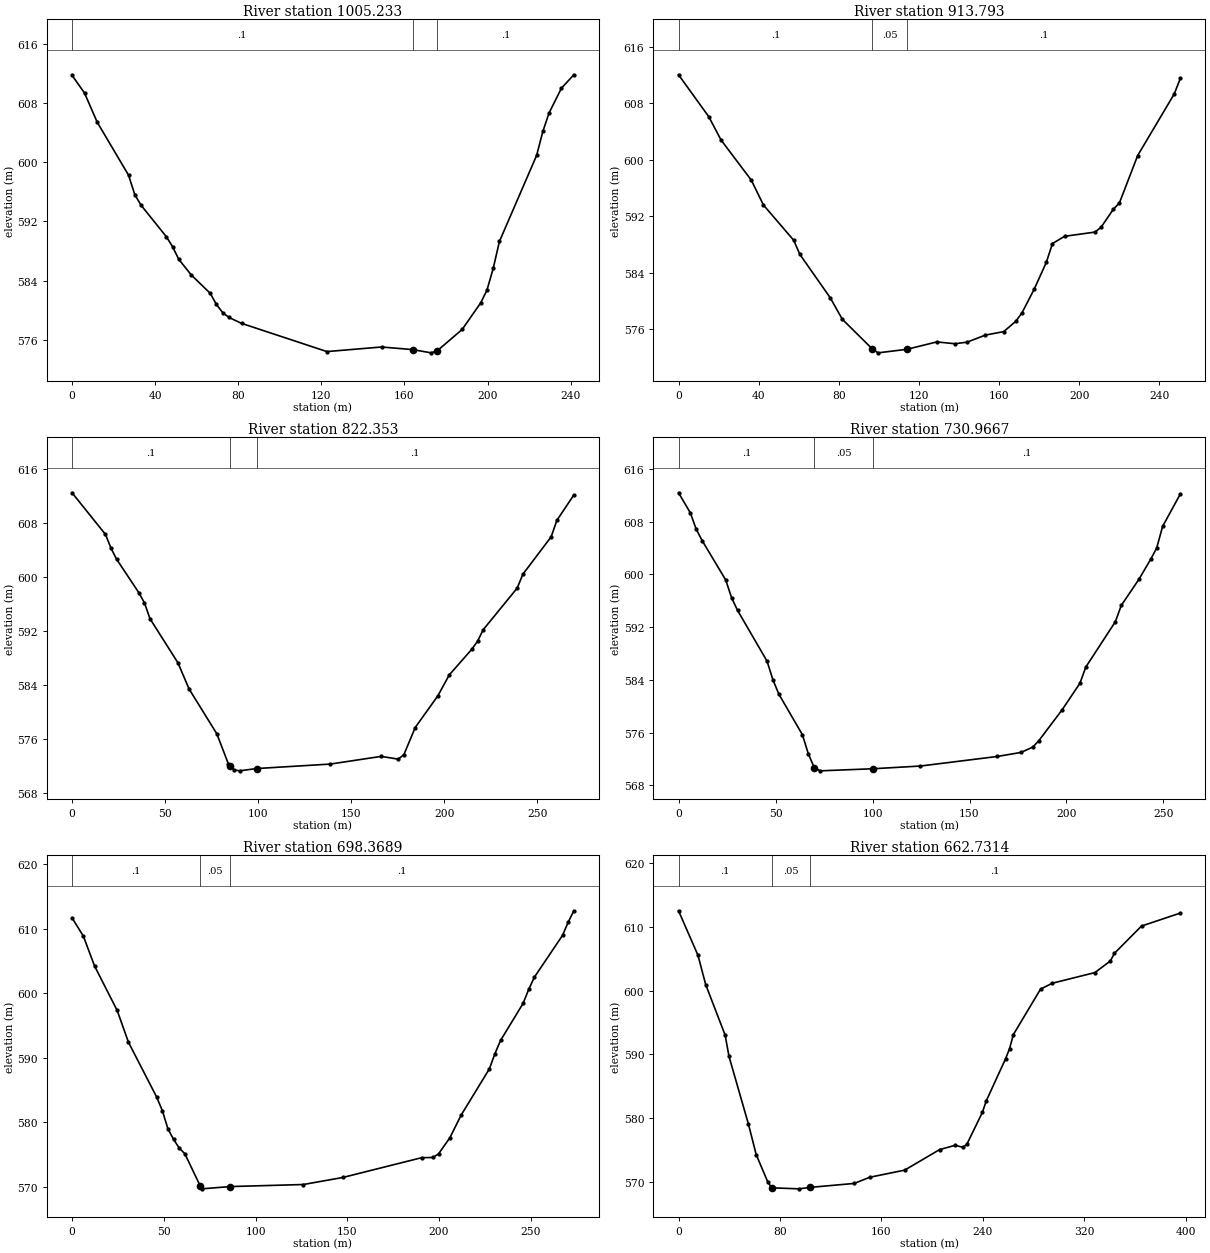
Type RM Length L Ch R = 1 ,1005.233,94.91,91.44,86.27
XS GIS Cut Line= 4
     622502.2479    4342096.7982     622412.8231    4342059.9929
     622380.1784    4342031.5336     622296.6662    4341973.7667
#Sta/Elev= 30
       0  611.73    6.04  609.31   12.09   605.4    27.2  598.23   30.22  595.59
   33.24  594.17   45.33  589.95   48.35   588.6   51.37  586.87   57.42  584.75
   66.48  582.29   69.51  580.77   72.53  579.67   75.55  579.02   81.59  578.22
  122.69  574.41  148.97  575.03   163.9  574.68  172.86  574.24  175.85  574.53
   187.8   577.4  196.76  581.01  199.74  582.72  202.73  585.64  205.72  589.28
  223.64  600.91  226.62  604.14  229.61  606.63  235.58  609.99  241.56   611.8
#Mann= 3 , 0 , 0
       0      .1       0   163.9     .05       0  175.85      .1       0
Bank Sta=163.9,175.85
XS Rating Curve= 0 ,0
Exp/Cntr=0.3,0.1

Type RM Length L Ch R = 1 ,913.793 ,94.86,91.44,83.84
XS GIS Cut Line= 4
     622522.8854    4342003.1355     622437.8454    4341963.5023
     622415.0904    4341951.0904     622295.8725    4341897.5666
#Sta/Elev= 30
       0  612.06   15.13   606.1   21.19  602.82   36.32  597.11   42.37  593.59
    57.5  588.58   60.53  586.59   75.66  580.45   81.72  577.39    96.7  573.17
   99.58  572.62  113.98  573.12  128.86  574.17  137.98  573.91  144.05  574.14
  153.17  575.14  162.29  575.63  168.37  577.11  171.41   578.3  177.49  581.65
  183.56  585.46   186.6  588.12  192.68  589.15  207.88  589.75  210.92  590.46
  216.99  592.98  220.03  593.89  229.15  600.61  247.38  609.34  250.42  611.54
#Mann= 3 , 0 , 0
       0      .1       0    96.7     .05       0  113.98      .1       0
Bank Sta=96.7,113.98
XS Rating Curve= 0 ,0
Exp/Cntr=0.3,0.1

Type RM Length L Ch R = 1 ,822.353 ,89.93,91.39,80.56
XS GIS Cut Line= 4
      622556.223    4341909.4729     622482.8634    4341883.5003
     622456.0488    4341877.9084     622292.6975    4341859.4665
#Sta/Elev= 30
       0  612.51   17.96  606.34   20.95  604.29   23.95  602.66   35.92   597.7
   38.91   596.2    41.9  593.85   56.87  587.35   62.86  583.47   77.82  576.81
   83.91  572.43      85   572.1   86.95  571.51      90  571.35   99.13  571.69
   138.7  572.35   166.1  573.49  175.23  573.08  178.27  573.74  184.36  577.76
  196.54  582.46  202.63  585.54  214.81  589.36  217.85  590.53  220.89  592.24
  239.16   598.4   242.2  600.45  257.43     606  260.47  608.43   269.6  612.19
#Mann= 3 , 0 , 0
       0      .1       0      85     .05       0   99.13      .1       0
Bank Sta=85,99.13
XS Rating Curve= 0 ,0
Exp/Cntr=0.3,0.1

Type RM Length L Ch R = 1 ,730.9667,30.08,32.6,40.06
XS GIS Cut Line= 3
     622557.3475    4341794.3789     622469.1913    4341797.1852
     622298.7168    4341795.7018
#Sta/Elev= 30
       0  612.39    6.08  609.35    9.12  606.86   12.17  605.14   24.33  599.16
   27.37  596.45   30.41  594.56   45.62  586.85   48.66  584.02    51.7  581.85
   63.87  575.68   66.91  572.78   69.95  570.71   72.99  570.21  100.38  570.53
  124.73  570.94  164.31  572.39  176.49     573  182.57   573.8  185.62  574.74
   197.8  579.49  206.93   583.5  209.97  585.96  225.19  592.83  228.24   595.3
  237.37  599.28  243.46  602.33   246.5  604.02  249.55  607.29  258.68  612.21
#Mann= 3 , 0 , 0
       0      .1       0   69.95     .05       0  100.38      .1       0
Bank Sta=69.95,100.38
XS Rating Curve= 0 ,0
Exp/Cntr=0.3,0.1

Type RM Length L Ch R = 1 ,698.3689,34.49,35.64,39.49
XS GIS Cut Line= 3
     622561.0504    4341780.6837     622441.1939    4341753.2993
      622290.778    4341759.2524
#Sta/Elev= 30
       0  611.68    6.15  608.85   12.29   604.2   24.59  597.32   30.74  592.39
    46.1   583.9   49.18  581.81   52.25  578.97   55.33  577.33    58.4     576
   61.47  575.11   69.76  570.17   70.69  569.67   86.06  570.02  126.02  570.34
  147.52  571.43  190.53   574.5  196.68  574.53  199.75   575.1  205.89  577.58
  212.04   581.1   227.4  588.25  230.47  590.63  233.54  592.68  245.83  598.43
   248.9  600.61  251.97  602.49  267.33  608.98  270.41  611.03  273.48  612.78
#Mann= 3 , 0 , 0
       0      .1       0   69.76     .05       0   86.06      .1       0
Bank Sta=69.76,86.06
XS Rating Curve= 0 ,0
Exp/Cntr=0.3,0.1

Type RM Length L Ch R = 1 ,662.7314,23.3,23.26,21.57
XS GIS Cut Line= 4
     622573.2268    4341757.2736     622478.5058    4341722.0839
     622457.3391    4341715.4693     622185.2587    4341729.5364
#Sta/Elev= 30
       0  612.55   15.31  605.56   21.43  600.94   36.74  593.01   39.81  589.65
   55.12  579.02   61.24  574.23   70.43   569.9   73.49  569.01   94.92  568.85
  103.82  569.08  138.53   569.7  150.77  570.67  178.32  571.79  205.87  575.02
  218.12  575.69  224.24  575.38   227.3  575.84  239.55  580.85  242.61  582.66
  257.91  589.31  260.98  590.87  264.04   593.1  285.46  600.24  294.65  601.16
  328.32  602.84  340.57  604.67  343.63  605.85  365.06  610.15  395.67  612.19
#Mann= 3 , 0 , 0
       0      .1       0   73.49     .05       0  103.82      .1       0
Bank Sta=73.49,103.82
XS Rating Curve= 0 ,0
Exp/Cntr=0.3,0.1

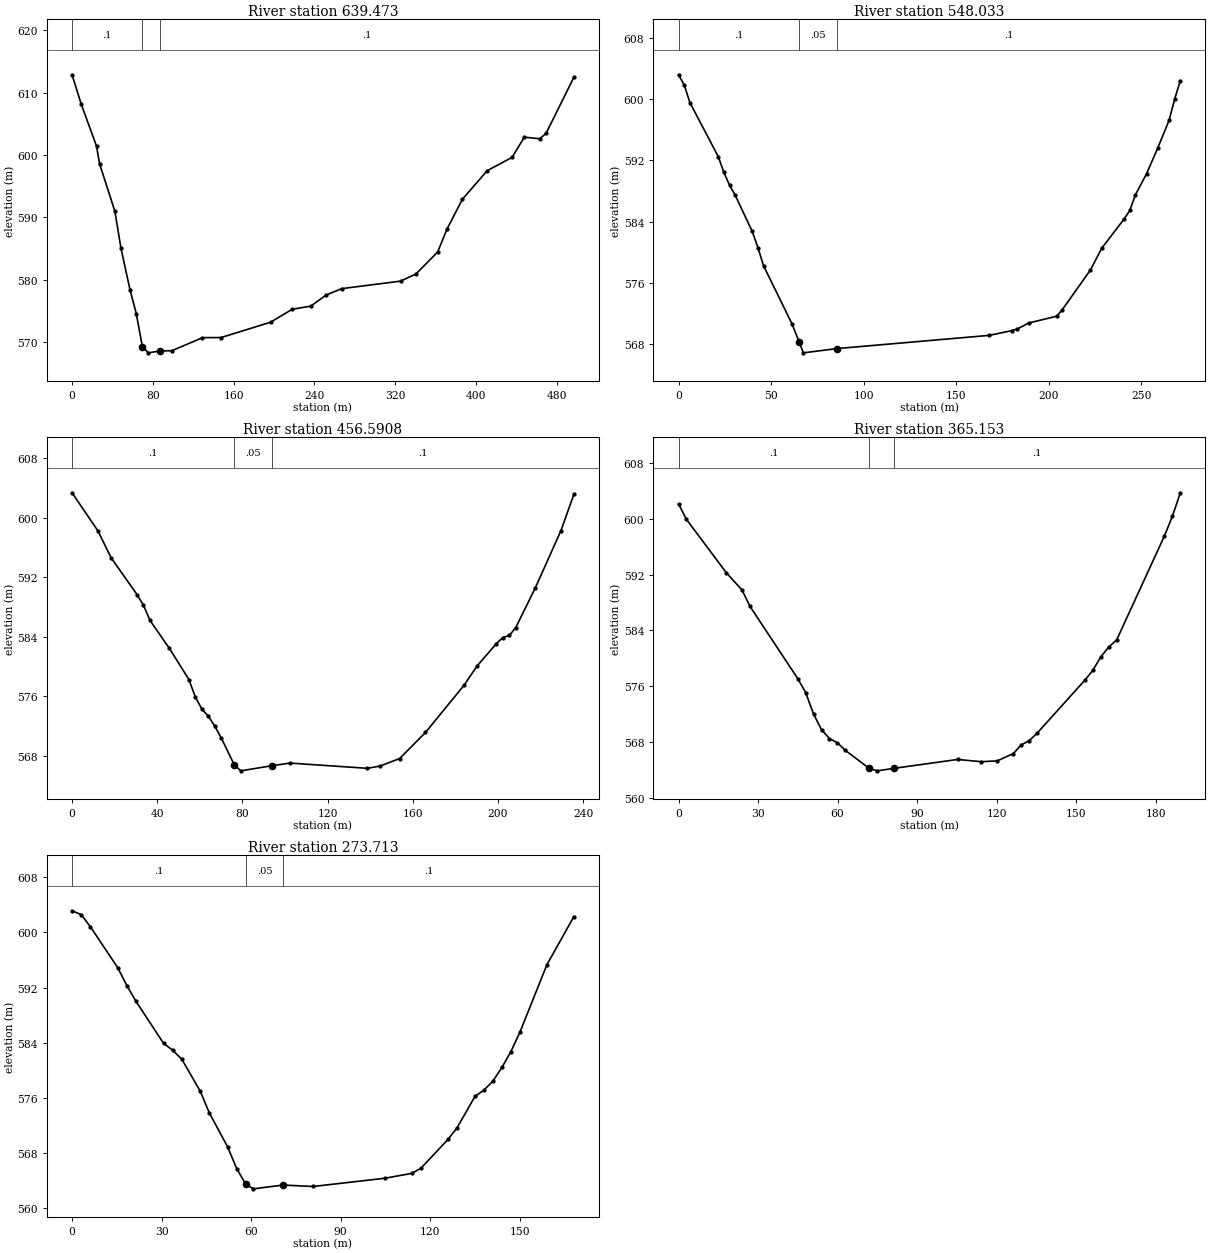
Type RM Length L Ch R = 1 ,639.473 ,92.82,91.44,86.02
XS GIS Cut Line= 4
     622582.4829    4341737.4933     622514.9758    4341710.6869
     622484.7463    4341700.2411     622098.9559    4341629.6754
#Sta/Elev= 30
       0  612.85    9.08  608.14   24.21  601.42   27.24  598.59   42.37  591.01
   48.42  585.07    57.5  578.33   63.56  574.62   69.61  569.33   75.54  568.33
   87.17  568.63    98.8  568.67  129.13  570.76  147.51  570.78  196.54  573.23
  217.99  575.31  236.37  575.81  251.69   577.6  267.01  578.61  325.23  579.81
  340.55  580.97  361.99  584.48  371.19  588.14  386.51  592.94  411.02   597.5
  435.53  599.61  447.78  602.86   463.1  602.61  469.23  603.45  496.81  612.44
#Mann= 3 , 0 , 0
       0      .1       0   69.61     .05       0   87.17      .1       0
Bank Sta=69.61,87.17
XS Rating Curve= 0 ,0
Exp/Cntr=0.3,0.1

Type RM Length L Ch R = 1 ,548.033 ,91.15,91.44,101.34
XS GIS Cut Line= 4
     622612.1935    4341644.3929     622553.5309    4341626.8042
     622511.1597    4341619.7552     622352.3722    4341568.7219
#Sta/Elev= 30
       0  603.16    3.06  601.84    6.12  599.54   21.43   592.5    24.5  590.43
   27.56  588.76   30.62  587.45   39.81  582.73   42.87  580.63   45.93  578.25
   61.24   570.7   65.24  568.28   67.38  566.91   85.79  567.47  167.88  569.19
  180.01  569.81  183.04  570.04  189.11   570.8  204.27  571.69   207.3  572.56
  222.46  577.72  228.53  580.54  240.66  584.37  243.69  585.47  246.72   587.5
  252.79  590.28  258.85  593.65  264.92  597.23  267.95  600.02  270.98   602.4
#Mann= 3 , 0 , 0
       0      .1       0   65.24     .05       0   85.79      .1       0
Bank Sta=65.24,85.79
XS Rating Curve= 0 ,0
Exp/Cntr=0.3,0.1

Type RM Length L Ch R = 1 ,456.5908,85.53,91.44,104.66
XS GIS Cut Line= 4
     622652.6748      4341565.15     622571.7619    4341537.9076
     622555.0675    4341534.8084     622448.4409    4341454.7429
#Sta/Elev= 30
       0  603.34    12.2   598.2   18.29  594.63   30.49  589.68   33.54  588.25
   36.59  586.21   45.74  582.44   54.88  578.27   57.93   575.9   60.98   574.3
   64.03  573.34   67.08  571.99   70.13  570.39   76.23  566.79   79.28  566.01
   93.87   566.7  102.36  567.05  138.72  566.35  144.78  566.66  153.87  567.66
     166  571.16  184.18  577.52  190.24  580.09  199.33   583.1  202.36  583.91
  205.39  584.18  208.42  585.25  217.51  590.52  229.64  598.26   235.7  603.13
#Mann= 3 , 0 , 0
       0      .1       0   76.23     .05       0   93.87      .1       0
Bank Sta=76.23,93.87
XS Rating Curve= 0 ,0
Exp/Cntr=0.3,0.1

Type RM Length L Ch R = 1 ,365.153 ,91.99,91.44,93.23
XS GIS Cut Line= 4
     622683.8693    4341519.9856     622633.7907    4341472.6209
     622617.2099    4341454.8027     622557.6628    4341379.4915
#Sta/Elev= 30
       0  602.12       3  599.89   17.98  592.28   23.98  589.76   26.97  587.42
   44.95   577.1   47.95  575.09   50.95  571.99   53.94  569.76   56.94   568.5
   59.94  567.88   62.94   566.8   71.97  564.21   75.01  563.87    81.1  564.22
  105.27   565.5  114.27  565.18  120.27   565.3  126.27  566.34  129.27  567.59
  132.27  568.19  135.27  569.27  153.27  576.86  156.27  578.26  159.27  580.19
  162.28  581.61  165.28  582.64  183.28  597.52  186.28  600.33  189.28  603.71
#Mann= 3 , 0 , 0
       0      .1       0   71.97     .05       0    81.1      .1       0
Bank Sta=71.97,81.1
XS Rating Curve= 0 ,0
Exp/Cntr=0.3,0.1

Type RM Length L Ch R = 1 ,273.713 ,255.2,273.71,250.31
XS GIS Cut Line= 5
      622740.821    4341466.1427     622706.8635    4341418.8652
       622700.11    4341411.2026     622695.4636     4341403.125
     622637.4348    4341333.8508
#Sta/Elev= 30
       0  603.14    3.06  602.58    6.13  600.83   15.32  594.87   18.38  592.28
   21.45  589.99   30.64  583.93    33.7  582.93   36.76  581.62   42.89  577.03
   45.95  573.87   52.08  568.94   55.15  565.77   58.21  563.49   60.76  562.83
   70.75  563.38   80.75  563.17  104.85  564.37  113.89  565.08   116.9  565.83
  125.94  569.99  128.95  571.66  134.97  576.22  137.99  577.15     141  578.45
  144.01  580.43  147.02  582.73  150.04  585.54  159.07  595.31  168.11   602.3
#Mann= 3 , 0 , 0
       0      .1       0   58.21     .05       0   70.75      .1       0
Bank Sta=58.21,70.75
XS Rating Curve= 0 ,0
Exp/Cntr=0.3,0.1
LCMann Table=0

Chan Stop Cuts=-1
Use User Specified Reach Order=0
Composite Channel Slope=5